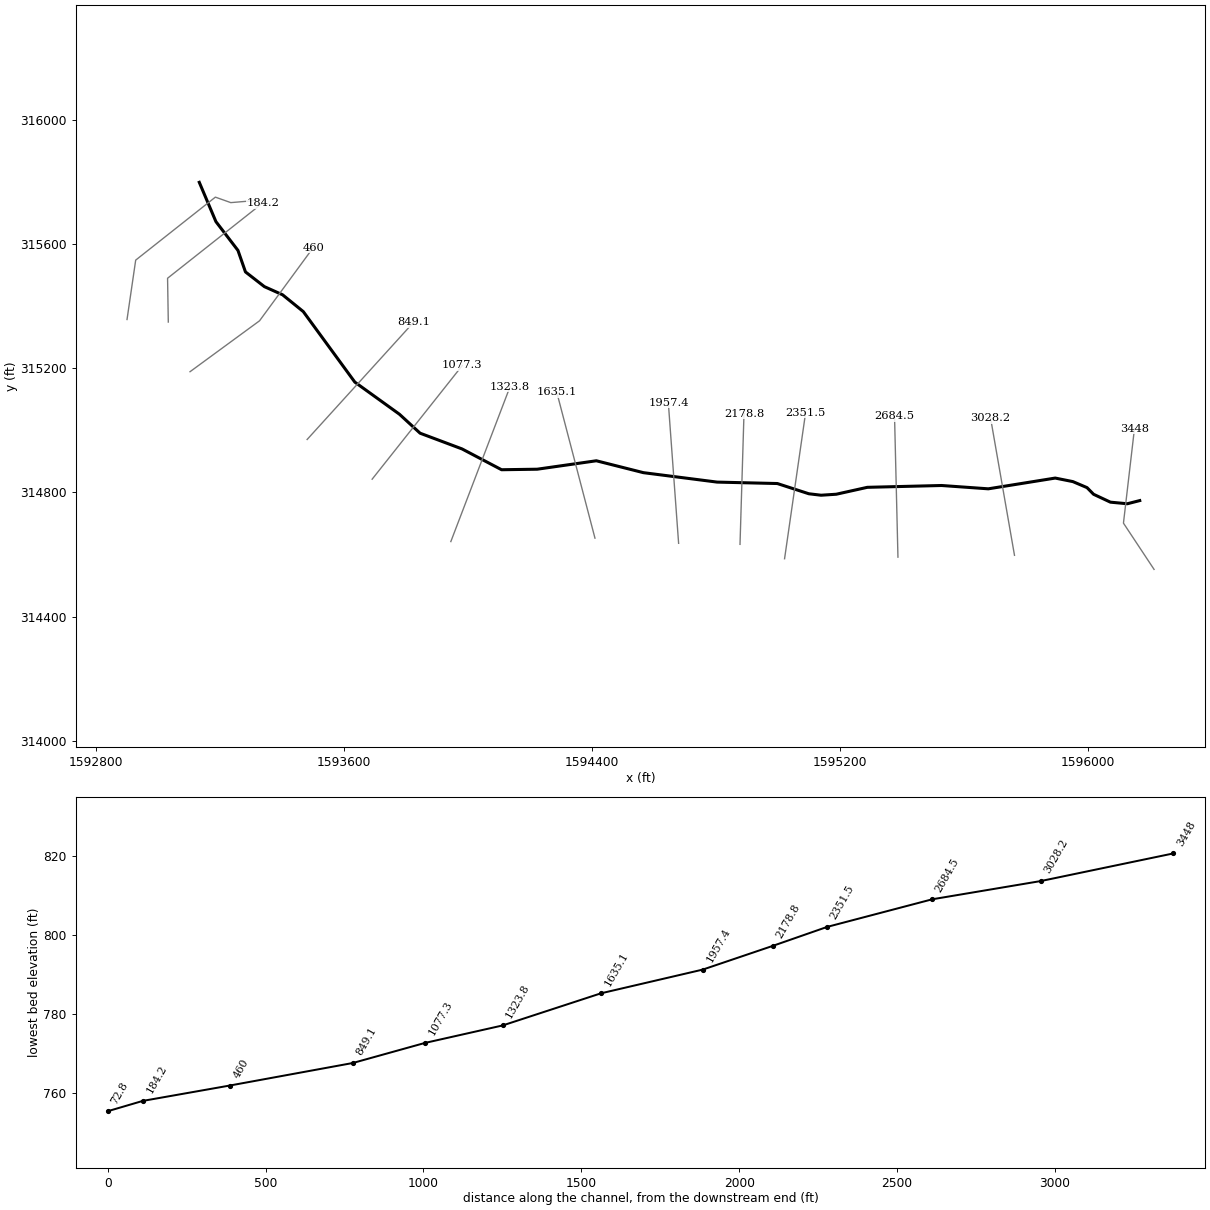
--- lrlbrnch1.prj (project) ---

Proj Title=lrlbrnch1
Current Plan=p01
Default Exp/Contr=0,0
English Units
Geom File=g01
Flow File=f01
Plan File=p01
BEGIN DESCRIPTION:
END DESCRIPTION:
DSS Export Rating Curves= 0
DSS Export Rating Curve Sorted= 0
DSS Export Volume Flow Curves= 0
DXF OffsetX= 0
DXF OffsetY= 0
DXF ScaleX= 0
DXF ScaleY= 0

--- lrlbrnch1.p01 (plan) ---

Plan Title=Approximate Study - 100yr
Program Version=4.00
Geom File=g01
Flow File=f01
Subcritical Flow
K Sum by GR= 0
Std Step Tol= 0.01
Critical Tol= 0.01
Num of Std Step Trials= 20
Max Error Tol= 0.3
Flow Tol Ratio= 0.001
Split Flow NTrial= 30
Split Flow Tol= 0.02
Split Flow Ratio= 0.02
Log Output Level= 0
Friction Slope Method= 1
Unsteady Friction Slope Method= 2
Unsteady Bridges Friction Slope Method= 1
Parabolic Critical Depth
Global Vel Dist= 0 , 0 , 0
Global Log Level= 0
CheckData=True
Encroach Param=-1 ,0,0, 0
Run HTab= 0
Run UNet= 0
Run PostProcess= 0
Run WQNet= 0
UNET Theta= 0
UNET Theta Warmup= 0
UNET ZTol= 0
UNET ZSATol= 0
UNET MxIter= 0
UNET MaxInSteps= 0
UNET DtIC= 0
UNET DtMin= 0
UNET MaxCRTS= 0
UNET WFStab= 0
UNET SFStab= 0
UNET WFX= 1
UNET SFX= 1
UNET DSS MLevel= 1
UNET DZMax Abort= 0
UNET Convert EG Bridges= 0
UNET Use Existing IB Tables= 0
UNET Froude Reduction=False
UNET Froude Limit= 0
UNET Froude Power= 0
UNET Time Slicing=0,0, 5
Write IC File= 0
Echo Input=False
Echo Output=False
Write Detailed= 0
Detailed Automatic Start=False, 0
WQ ULTIMATE=-1
WQ Max Comp Step=1HOUR
WQ Output Interval=15MIN
WQ Output Selected Increments= 0
WQ Output face flow=0
WQ Output face velocity=0
WQ Output face area=0
WQ Output face dispersion=0
WQ Output cell volume=0
WQ Output cell surface area=0
WQ Output cell continuity=0
WQ Output face conc=0
WQ Output face dconc_dx=0
WQ Output face courant=0
WQ Output face peclet=0
WQ Output face adv mass=0
WQ Output face disp mass=0
WQ Output cell mass=0
WQ Output cell source sink temp=0
WQ Output cell source sink nsm=0
WQ Output MaxMinRange=-1
WQ Daily Max Min Mean=-1
WQ Daily Range=0
WQ Daily Time=0
WQ Create Restart=0
WQ Fixed Restart=0
WQ System Summary=False
Sorting and Armoring Iterations= 10
XS Update Threshold= 0.02
Hydraulics Update Threshold= 0.02
Energy Slope Method= 1
Volume Change Method= 0
XS Weighting Method= 0
Number of US Weighted Cross Sections= 1
Number of DS Weighted Cross Sections= 1
Upstream XS Weight=0.25
Main XS Weight=0.5
Downstream XS Weight=0.25
Number of DS XS's Weighted with US Boundary= 1
Upstream Boundary Weight= 1
Weight of XSs Associated with US Boundary= 0
Number of US XS's Weighted with DS Boundary= 1
Downstream Boundary Weight= 0.5
Weight of XSs Associated with DS Boundary= 0.5
Sediment Output Level= 4
Mass or Volume Output= 0
Output Increment Type= 1
Profile and TS Output Increment= 10
XS Output Flag= 0
XS Output Increment= 10
Disregard all LS=0
Disregard all Conn=0
Disregard all Breaches=0
Disregard all Pumps=0

--- lrlbrnch1.f01 (steady flow) ---

Flow Title=NFF Regression Equation
Program Version=4.00
Number of Profiles=1
Profile Names=P100yr
River Rch & RM=lrlbrnch1,Main      ,3448
     300
River Rch & RM=lrlbrnch1,Main      ,3028.2
     420
River Rch & RM=lrlbrnch1,Main      ,2351.5
     440
River Rch & RM=lrlbrnch1,Main      ,184.2
     484
Boundary for River Rch & Prof#=lrlbrnch1,Main      ,1
Up Type=0
Dn Type=3
Dn Slope=0.017447

--- lrlbrnch1.g01 (geometry) ---

Geom Title=USGS 3m DEM
Program Version=4.00

River Reach=lrlbrnch1       ,Main
Reach XY= 30
     1596165.914       314773.71     1596125.889      314763.522
     1596071.362      314768.616     1596017.069      314794.035
     1595995.926      314815.513     1595950.358       314834.89
     1595893.451      314846.304     1595677.674      314811.643
     1595527.049      314822.351     1595287.714       314816.47
       1595187.5      314794.181     1595138.666      314791.017
      1595099.09       314795.72     1594997.566      314828.699
     1594803.585        314833.3     1594565.919      314863.726
     1594414.132       314902.05     1594223.578      314874.862
     1594108.696      314873.173     1593981.271      314940.217
     1593846.019      314990.949     1593779.547      315052.012
     1593635.647      315155.613     1593469.523      315382.903
     1593402.715      315437.135     1593344.082      315463.414
     1593283.084      315510.849     1593258.887      315580.173
     1593187.877      315672.925     1593134.221      315799.675

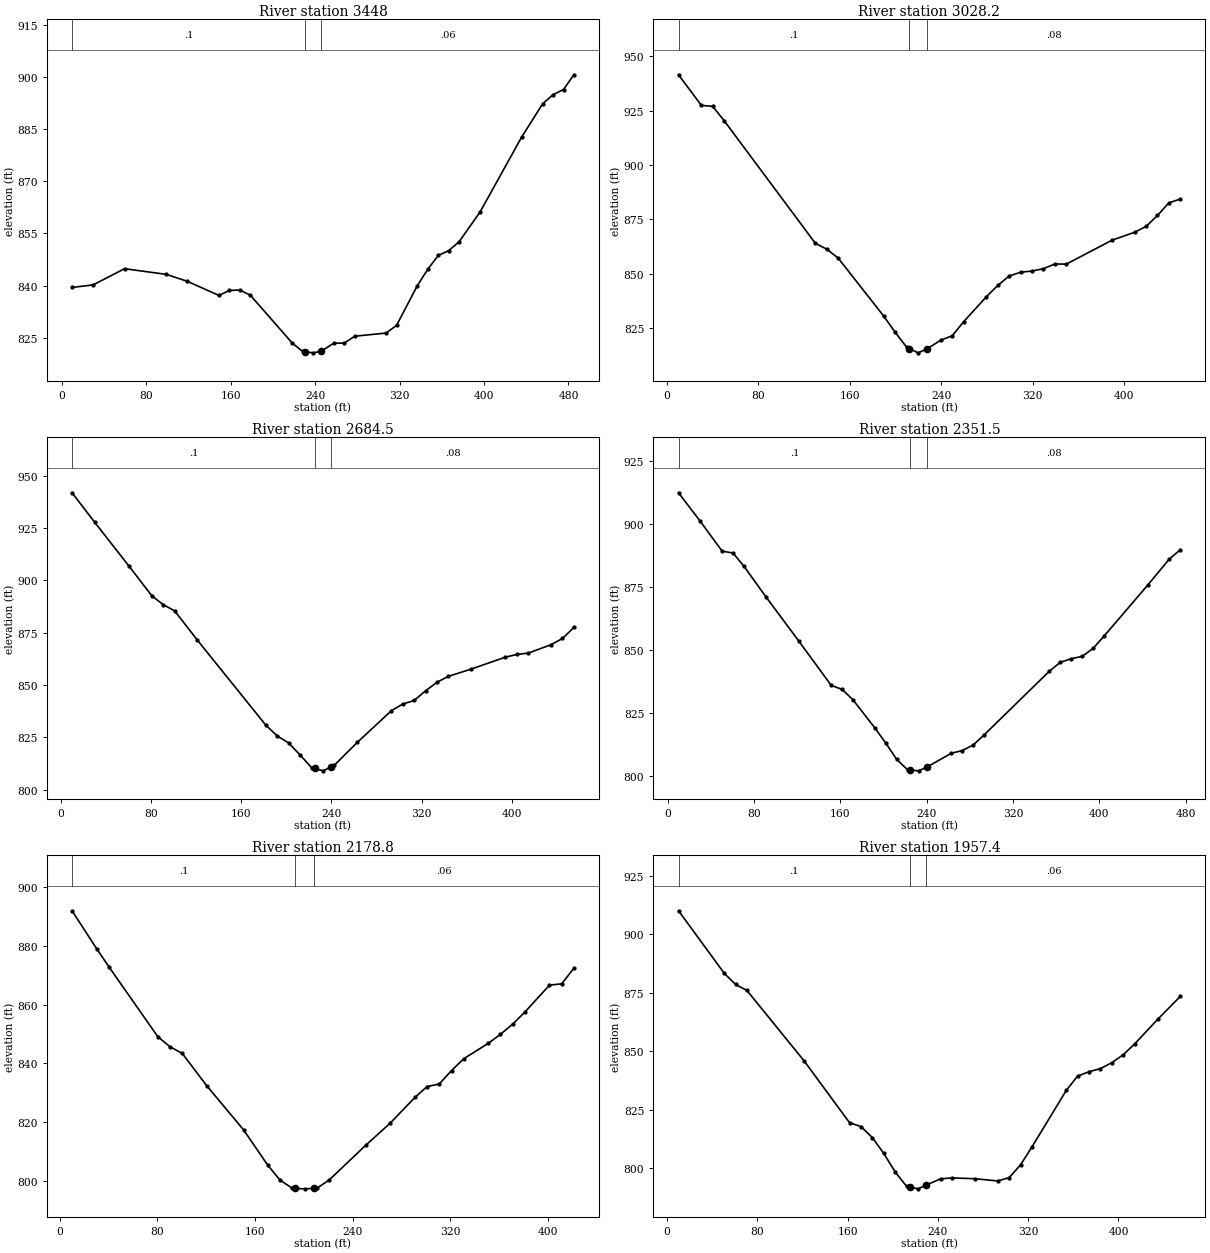
Type RM Length L Ch R = 1 ,3448    ,413.3,419.8,426.3
XS GIS Cut Line= 3
     1596212.049      314551.915     1596113.368      314701.019
     1596148.835      315005.304
#Sta/Elev= 30
     9.9  839.46    29.8  840.18    59.6  844.86    99.3  843.21   119.2   841.2
     149  837.16   158.9  838.61   168.9   838.7   178.8   837.2   218.3  823.49
   228.2  821.04   230.6  820.94   238.1  820.64   245.6  821.07   257.9  823.43
   267.7  823.44   277.6  825.43   307.3  826.33   317.2  828.54   336.9  839.99
   346.8  844.71   356.7  848.67   366.6  850.05   376.4  852.62   396.2  861.13
   435.7  882.75   455.5   892.3   465.4  894.93   475.3  896.42   485.1  900.66
#Mann= 3 , 0 , 0
     9.9      .1       0   230.6    .045       0   245.6     .06       0
Bank Sta=230.6,245.6
XS Rating Curve= 0 ,0
Exp/Cntr=0.3,0.1

Type RM Length L Ch R = 1 ,3028.2  ,347,343.7,340.4
XS GIS Cut Line= 2
     1595762.134      314597.308     1595684.983       315039.94
#Sta/Elev= 30
      10   941.5      30  927.41    39.9  926.99    49.9  920.41   129.8  863.99
   139.8  861.31   149.8  857.18   189.7  830.48   199.7  823.06   209.7  816.26
   212.2   815.6   219.7  813.64   227.2  815.37   239.6  819.46   249.6  821.49
   259.6  827.94   279.6  839.49   289.6  844.69   299.5  848.98   309.5  850.71
   319.5  851.26   329.5  852.36   339.5   854.5   349.5  854.44   389.4  865.41
   409.4  869.11   419.4  871.79   429.3  876.81   439.3  882.63   449.3  884.35
#Mann= 3 , 0 , 0
      10      .1       0   212.2    .045       0   227.2     .08       0
Bank Sta=212.2,227.2
XS Rating Curve= 0 ,0
Exp/Cntr=0.3,0.1

Type RM Length L Ch R = 1 ,2684.5  ,336.7,333,329.3
XS GIS Cut Line= 2
     1595386.453       314591.38      1595375.44      315046.247
#Sta/Elev= 30
    10.1  941.89    30.3   927.7    60.7  906.76    80.9  892.61      91  888.41
   101.1  885.45   121.3   871.4     182  830.77   192.1  825.65   202.2  822.31
   212.3  816.59   222.4   810.6   225.1  810.18   232.6  809.02   240.1  811.04
   242.7  811.74   262.9  822.57   293.2  837.75   303.3  840.96   313.4  842.64
   323.6  847.29   333.7  851.37   343.8  854.17     364  857.65   394.3  863.34
   404.4  864.63   414.6  865.28   434.8  869.31   444.9  872.26     455  877.54
#Mann= 3 , 0 , 0
    10.1      .1       0   225.1    .045       0   240.1     .08       0
Bank Sta=225.1,240.1
XS Rating Curve= 0 ,0
Exp/Cntr=0.3,0.1

Type RM Length L Ch R = 1 ,2351.5  ,170.2,172.7,175.2
XS GIS Cut Line= 2
     1595020.946      314586.245     1595088.704      315056.402
#Sta/Elev= 30
    10.1  912.45    30.3  901.08    50.5  889.28    60.6  888.52    70.7  883.27
      91  871.16   121.3  853.69   151.6  835.94   161.7  834.36   171.8  830.19
     192  819.05   202.1  813.06   212.2  806.57   222.3  802.46     225  802.34
   232.5  802.02     240  803.47   262.8     809   272.9  810.07     283  812.24
   293.1  816.24   353.7  841.61   363.8  845.12   373.9  846.55   384.1  847.48
   394.2  850.66   404.3  855.51   444.7  875.73   464.9  886.19     475  889.82
#Mann= 3 , 0 , 0
    10.1      .1       0     225    .045       0     240     .08       0
Bank Sta=225,240
XS Rating Curve= 0 ,0
Exp/Cntr=0.3,0.1

Type RM Length L Ch R = 1 ,2178.8  ,219,221.4,223.7
XS GIS Cut Line= 2
     1594877.299      314632.597     1594890.138      315053.946
#Sta/Elev= 30
      10  891.97    30.1  879.08    40.1  872.94    80.3  849.07    90.3  845.63
   100.4  843.34   120.4  832.35   150.6  817.33   170.6  805.19   180.7  800.12
   190.7  797.39   193.2  797.34   200.7   797.2   208.2  797.36   210.8  797.41
   220.8   800.2   250.9  812.08     271  819.63   291.1  828.34   301.1  832.05
   311.1  832.94   321.2  837.51   331.2  841.55   351.3  846.78   361.3  849.86
   371.4  853.35   381.4  857.48   401.5  866.62   411.5  867.08   421.5  872.38
#Mann= 3 , 0 , 0
      10      .1       0   193.2    .045       0   208.2     .06       0
Bank Sta=193.2,208.2
XS Rating Curve= 0 ,0
Exp/Cntr=0.3,0.1

Type RM Length L Ch R = 1 ,1957.4  ,318.1,322.3,326.5
XS GIS Cut Line= 2
     1594679.391      314636.027     1594646.204      315089.589
#Sta/Elev= 30
    10.1  910.08    50.5  883.43    60.6  878.58    70.7  876.02   121.3  845.96
   161.7  819.45   171.8  817.82   181.9  813.08     192  806.31   202.1  798.42
   212.2  792.25   214.8  791.98   222.3   791.2   229.8  792.87   242.5  795.49
   252.7  795.87   272.9  795.52   293.1  794.56   303.2  796.04   313.3  801.52
   323.4   809.2   353.7  833.25   363.8  839.43   373.9  841.28     384  842.61
   394.1  845.13   404.2  848.54   414.4  853.19   434.6  863.62   454.8  873.47
#Mann= 3 , 0 , 0
    10.1      .1       0   214.8    .045       0   229.8     .06       0
#XS Ineff= 2 , 0
       0                   252.7       0  795.87
Permanent Ineff=
       F       F
Bank Sta=214.8,229.8
XS Rating Curve= 0 ,0
Exp/Cntr=0.3,0.1

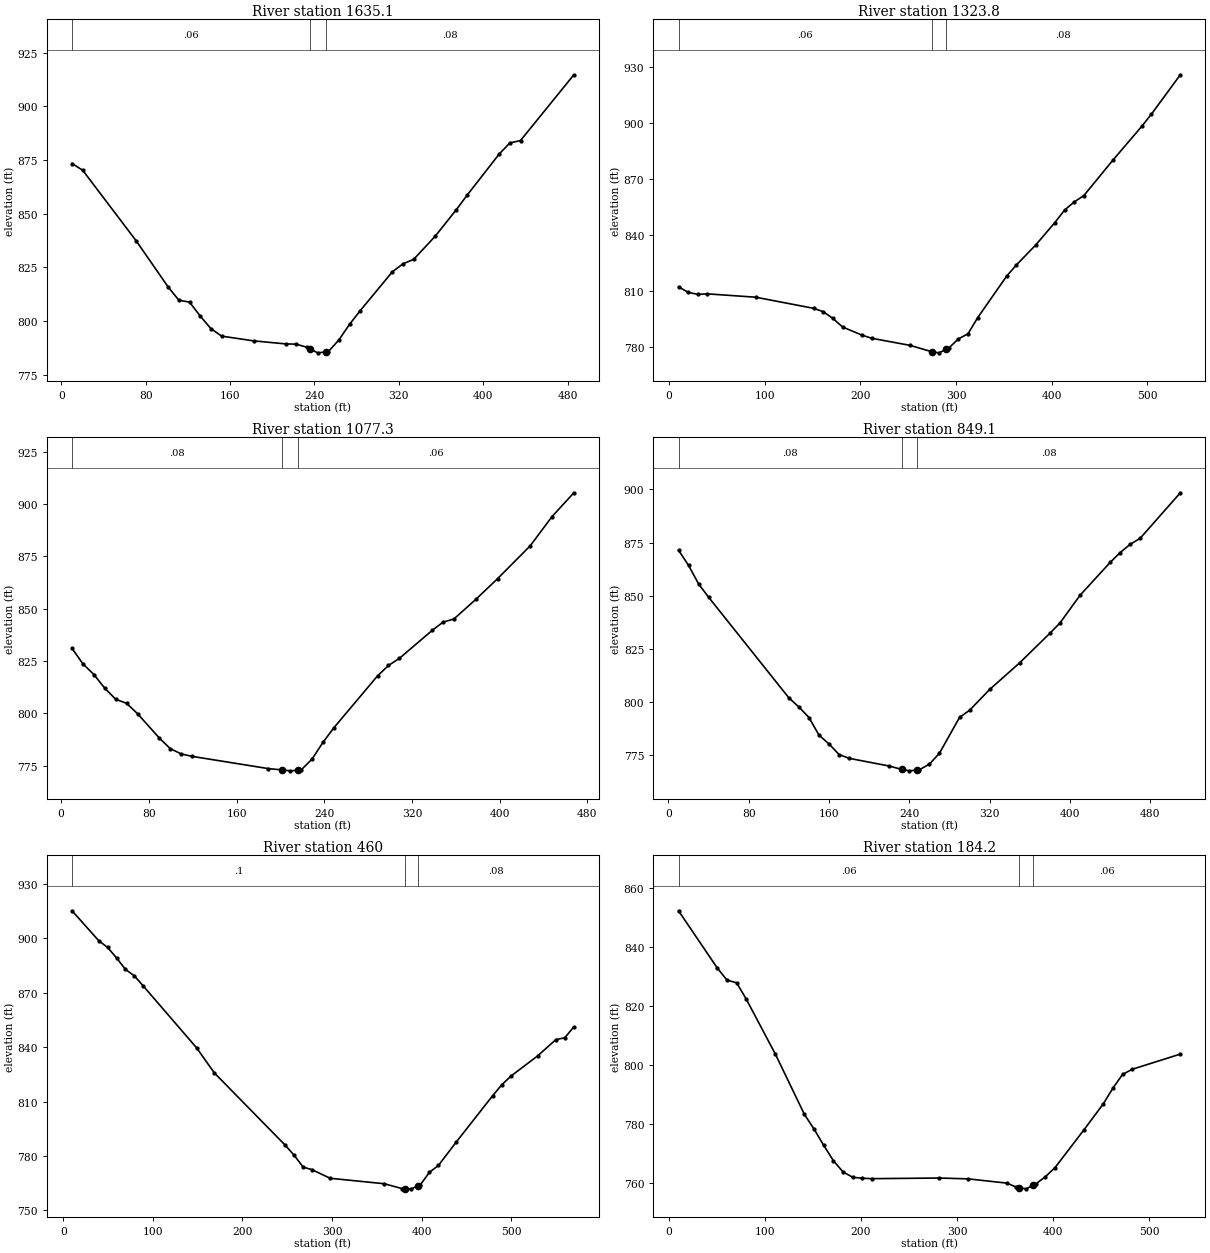
Type RM Length L Ch R = 1 ,1635.1  ,325.5,311.3,297.1
XS GIS Cut Line= 2
     1594409.743      314652.621     1594286.672      315122.777
#Sta/Elev= 30
    10.1  873.37    20.2  870.22    70.9  837.36   101.2  815.89   111.4  809.69
   121.5  808.82   131.6  802.35   141.7  796.51   151.9  792.98   182.2  790.77
   212.6  789.36   222.7  789.23   232.9  787.77   235.5  787.11     243  785.19
   250.5  785.58   253.1  785.71   263.2  791.24   273.4  798.55   283.5   804.9
   313.9  822.95     324  826.68   334.1  828.74   354.4  839.46   374.6   851.9
   384.7  858.58   415.1  877.73   425.2  882.93   435.4  884.07     486   914.7
#Mann= 3 , 0 , 0
    10.1     .06       0   235.5    .045       0   250.5     .08       0
Bank Sta=235.5,250.5
XS Rating Curve= 0 ,0
Exp/Cntr=0.3,0.1

Type RM Length L Ch R = 1 ,1323.8  ,253.4,246.5,239.6
XS GIS Cut Line= 2
     1593945.118      314641.558     1594135.946      315140.753
#Sta/Elev= 30
    10.1  812.32    20.2  809.36    30.3  808.29    40.3  808.56    90.8  806.77
   151.3  800.83   161.3  799.04   171.4  795.42   181.5  790.86   201.7  786.52
   211.8  784.85   252.1  781.03   274.8  777.63   282.3  777.05   289.8  778.93
   292.4  779.58   302.5  784.47   312.6  787.28   322.7  795.86   352.9  818.02
     363  823.94   383.2  834.61   403.3  846.65   413.4  853.29   423.5  857.68
   433.6  861.07   463.8  879.91   494.1  898.08   504.2   904.6   534.4  925.62
#Mann= 3 , 0 , 0
    10.1     .06       0   274.8    .045       0   289.8     .08       0
Bank Sta=274.8,289.8
XS Rating Curve= 0 ,0
Exp/Cntr=0.3,0.1

Type RM Length L Ch R = 1 ,1077.3  ,229.7,228.2,226.7
XS GIS Cut Line= 2
      1593691.45      314842.688     1593982.076      315209.181
#Sta/Elev= 30
      10  831.07    19.9  823.68    29.9  818.61    39.8  812.09    49.8  806.78
    59.7  804.86    69.7   799.9    89.6  788.27    99.5  783.25   109.5  780.69
   119.4  779.53   189.1  773.67   201.5  773.05     209  772.61   216.5  772.92
   218.9  773.02   228.9  778.24   238.8  786.17   248.8  793.18   288.6  817.94
   298.6  822.92   308.5  826.29   338.4  839.64   348.3   843.6   358.3  845.13
   378.2  854.45   398.1  864.37   427.9  880.07   447.8  894.03   467.7  905.39
#Mann= 3 , 0 , 0
      10     .08       0   201.5    .045       0   216.5     .06       0
Bank Sta=201.5,216.5
XS Rating Curve= 0 ,0
Exp/Cntr=0.3,0.1

Type RM Length L Ch R = 1 ,849.1   ,386.7,389,391.3
XS GIS Cut Line= 2
     1593481.876      314970.667     1593824.813      315348.175
#Sta/Elev= 30
      10  871.38      20  864.23      30  855.51      40  849.24     120  801.85
     130  797.57     140  792.61     150  784.31     160  780.16     170   775.2
     180  773.42     220  769.79   232.5  768.18     240  767.53   247.5   767.9
     250  768.03     260  770.69     270  775.83     290  792.68     300  796.03
     320  805.83     350  818.42     380  832.27     390  837.08     410  850.14
     440  865.61     450  870.26     460  874.16     470  877.01     510  898.43
#Mann= 3 , 0 , 0
      10     .08       0   232.5    .045       0   247.5     .08       0
Bank Sta=232.5,247.5
XS Rating Curve= 0 ,0
Exp/Cntr=0.3,0.1

Type RM Length L Ch R = 1 ,460     ,282,275.9,269.8
XS GIS Cut Line= 3
     1593104.368      315189.152      1593328.46      315353.282
     1593501.235      315588.784
#Sta/Elev= 30
     9.9  915.27    39.7  898.74    49.6  895.02    59.5  889.28    69.4  882.96
    79.4  879.36    89.3  873.81   148.8  839.69   168.6  825.85     248   785.8
   257.9  780.25   267.8  773.83   277.8  772.38   297.9  767.66   358.3  764.65
   378.5  761.92   381.1  761.89   388.6  761.83   396.1  763.52   398.6  764.08
   408.7  770.92   418.8  774.77   438.9  787.82   479.2  813.17   489.3  819.14
   499.4  823.93   529.6  835.24   549.7  844.14   559.8  845.22   569.9  851.23
#Mann= 3 , 0 , 0
     9.9      .1       0   381.1    .045       0   396.1     .08       0
Bank Sta=381.1,396.1
XS Rating Curve= 0 ,0
Exp/Cntr=0.3,0.1

Type RM Length L Ch R = 1 ,184.2   ,111.2,111.4,111.5
XS GIS Cut Line= 3
     1593034.331      315349.241     1593031.996       315490.47
     1593338.963      315733.242
#Sta/Elev= 30
    10.1  852.26    50.4  832.86    60.5  828.76    70.6  827.81    80.7  822.25
     111  803.59   141.2  783.16   151.3  778.17   161.3  772.67   171.4  767.46
   181.4  763.67   191.4  761.86   201.5  761.53   211.5  761.38   281.7   761.6
   311.8  761.31     352  759.87     362  758.47   364.6  758.33   372.1  757.93
   379.6  759.18   382.1  759.59   392.1  762.04   402.2  765.16   432.3  777.97
   452.3  786.72   462.4  792.09   472.4  796.72   482.4  798.48   532.6  803.64
#Mann= 3 , 0 , 0
    10.1     .06       0   364.6    .045       0   379.6     .06       0
Bank Sta=364.6,379.6
XS Rating Curve= 0 ,0
Exp/Cntr=0.3,0.1

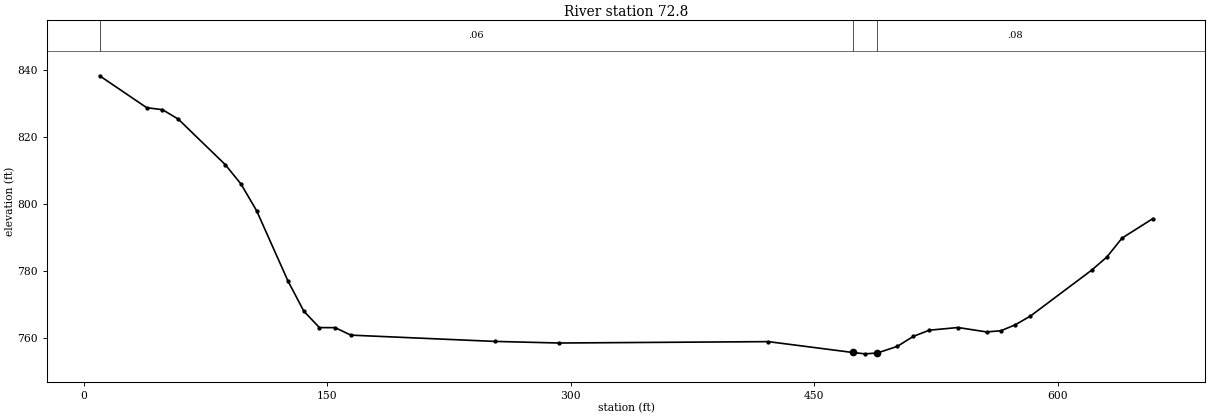
Type RM Length L Ch R = 1 ,72.8    ,79.7,72.8,65.9
XS GIS Cut Line= 5
     1592901.273      315357.412     1592929.236      315548.891
     1593186.063      315751.917      1593235.85      315734.229
     1593320.288      315741.412
#Sta/Elev= 30
     9.7  838.26    38.7  828.74    48.4  828.15    58.1  825.35    87.1  811.75
    96.8  805.96   106.4  798.01   125.8  776.97   135.5  768.03   145.1  763.14
   154.8  763.12   164.5  760.89     253  759.02   292.7  758.54   421.7  758.95
   473.7  755.71   481.2  755.31   488.7  755.55   501.1  757.53     511  760.52
   520.9  762.37   538.5  763.16   556.1  761.85   564.9  762.19   573.7  763.95
   583.1  766.57   620.8  780.25   630.2  784.18   639.6  789.85   658.5  795.63
#Mann= 3 , 0 , 0
     9.7     .06       0   473.7    .045       0   488.7     .08       0
Bank Sta=473.7,488.7
XS Rating Curve= 0 ,0
Exp/Cntr=0.3,0.1

Chan Stop Cuts=-1
Use User Specified Reach Order=0